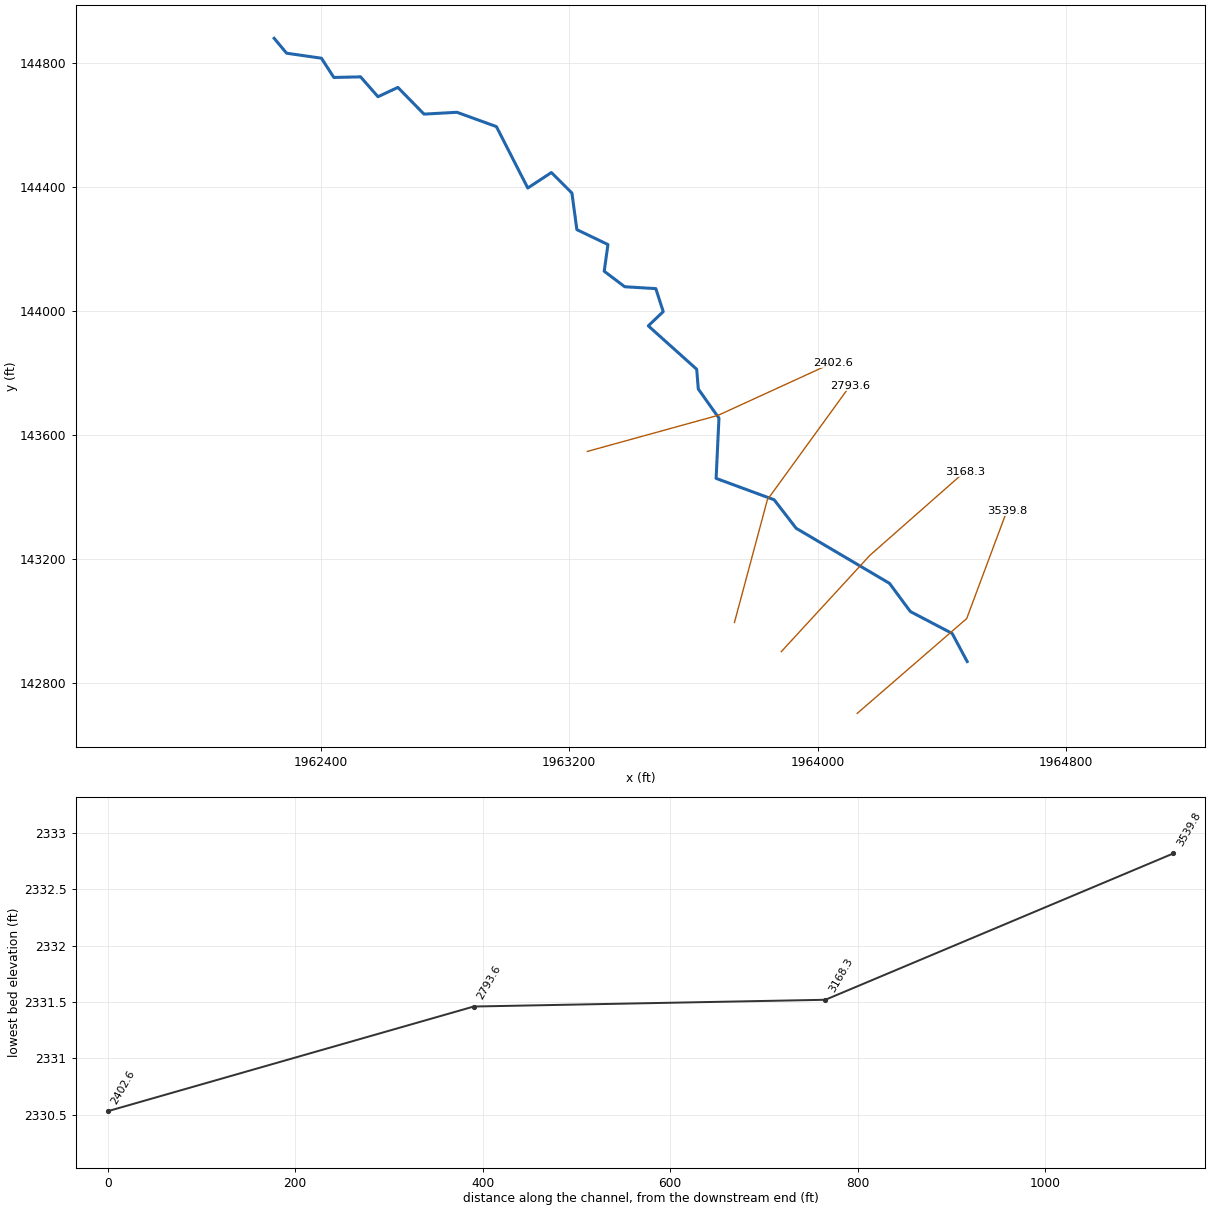
--- SprcFrk.prj (project) ---

Proj Title=SprcFrk
Current Plan=p01
Default Exp/Contr=0,0
English Units
Geom File=g01
Flow File=f01
Plan File=p01
BEGIN DESCRIPTION:
END DESCRIPTION:
DSS Export Rating Curves= 0
DSS Export Rating Curve Sorted= 0
DSS Export Volume Flow Curves= 0
DXF OffsetX= 0
DXF OffsetY= 0
DXF ScaleX= 0
DXF ScaleY= 0

--- SprcFrk.p01 (plan) ---

Plan Title=Floodplain
Program Version=4.00
Geom File=g01
Flow File=f01
K Sum by GR=0
Std Step Tol=0.01
Critical Tol=0.01
Num of Std Step Trials=20
Max Error Tol=0.3
Flow Tol Ratio=0.001
Split Flow NTrial=30
Split Flow Tol=0.02
Split Flow Ratio=0.02
Log Output Level=0
Friction Slope Method=1
Unsteady Friction Slope Method=2
Unsteady Bridges Friction Slope Method=1
Global Log Level=0
CheckData=False
Run HTab=0
Run UNet=0
Run PostProcess=0
UNET Theta=0
UNET Theta Warmup=0
UNET ZTol=0
UNET ZSATol=0
UNET MxIter=0
UNET MaxInSteps=0
UNET DtIC=0
UNET DtMin=0
UNET MaxCRTS=0
UNET WFStab=0
UNET SFStab=0
UNET WFX=0
UNET SFX=0
UNET DSS MLevel=0
UNET DZMax Abort=0
UNET Convert EG Bridges=0
UNET Use Existing IB Tables=0
UNET Froude Limit=0
UNET Froude Power=0
Write IC File=0
Echo Input=False
Echo Output=False
Write Detailed=0

--- SprcFrk.f01 (steady flow) ---

Flow Title=NFF Regression Equation
Program Version=4.00
Number of Profiles=1
Profile Names=P100yr
River Rch & RM=SprcFrk,Main      ,3539.8
626.0708
Boundary for River Rch & Prof#=SprcFrk,Main      ,1
Up Type=0
Dn Type=3
Dn Slope=0.001778

--- SprcFrk.g01 (geometry) ---

Geom Title=USGS 3m DEM
Program Version=4.10

River Reach=SprcFrk         ,Main
Reach XY= 30
     1964480.945      142869.944     1964432.697       142960.41
     1964298.073      143031.125      1964230.99      143122.047
     1963930.612      143299.657     1963859.747      143391.631
     1963673.055      143460.523     1963682.188      143654.823
     1963615.781      143748.573     1963610.573      143812.375
     1963454.845      143952.389     1963502.905      143998.382
     1963478.941      144072.451     1963378.888      144078.514
     1963312.931      144128.558     1963324.975      144214.588
      1963224.95      144262.673     1963209.033      144380.727
     1963143.061      144446.793     1963066.975       144396.85
     1962966.042      144594.927      1962839.05      144641.083
     1962733.011      144635.182     1962649.014      144721.281
     1962584.979      144691.242     1962528.983      144755.317
     1962442.933      144753.394     1962402.973      144815.451
     1962290.897      144831.547     1962250.935      144879.548

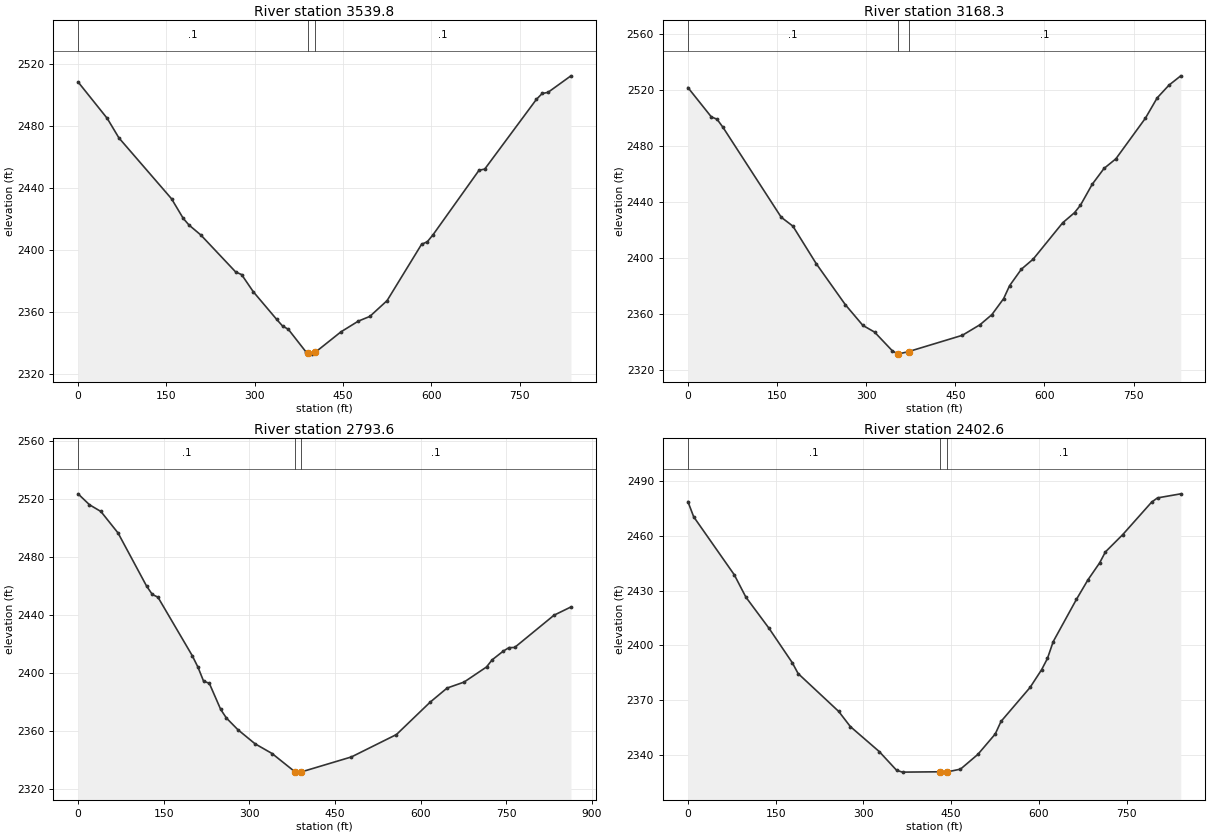
Type RM Length L Ch R = 1 ,3539.8  ,368.1,371.3,374.5
XS GIS Cut Line= 3
     1964127.137      142702.744     1964479.355      143008.373
     1964608.798      143355.968
#Sta/Elev= 30
       0 2508.22    49.6 2484.71    69.4 2472.16   158.8 2432.93   178.6 2420.33
   188.5 2415.99   208.4 2409.64   267.9  2385.7   277.8 2384.08   297.7    2373
   337.4 2355.19   347.3 2350.97   357.2  2348.8     387 2334.33   390.7 2333.77
   396.9 2332.82   402.7 2333.93   446.5 2347.16   476.1  2354.1   495.6 2357.12
   524.9  2367.3   583.5  2403.6   593.2 2405.22     603 2409.76   681.1 2451.31
   690.8 2452.07   778.7 2497.07   788.4 2500.78   798.2 2501.49   837.2 2512.16
#Mann= 3 , 0 , 0
       0      .1       0   390.7    .045       0   402.7      .1       0
Bank Sta=390.7,402.7
XS Rating Curve= 0 ,0
Exp/Cntr=0.3,0.1

Type RM Length L Ch R = 1 ,3168.3  ,366.7,375.1,378
XS GIS Cut Line= 3
     1963882.676        142901.7     1964168.077      143212.616
     1964473.467      143482.101
#Sta/Elev= 30
       0 2522.04    39.3 2501.12    49.1 2499.34    58.9 2493.68     157 2429.35
   176.7 2422.97   215.9 2396.19     265  2366.8   294.4 2352.05   314.1 2347.27
   343.5  2334.1   353.3 2331.52   371.5 2333.36   461.8 2344.98   491.6 2352.57
   511.4 2359.71   531.3 2371.21   541.2 2380.39   561.1 2392.22     581 2399.42
   630.7 2425.42   650.5 2432.59   660.5 2437.93   680.3  2452.9   700.2 2464.23
   720.1 2471.09   769.7 2500.06   789.6 2514.64   809.5 2523.76   829.3  2530.4
#Mann= 3 , 0 , 0
       0      .1       0   353.3    .045       0   371.5      .1       0
Bank Sta=353.3,371.5
XS Rating Curve= 0 ,0
Exp/Cntr=0.3,0.1

Type RM Length L Ch R = 1 ,2793.6  ,410.2,390.5,379.5
XS GIS Cut Line= 3
     1963732.023      142995.829     1963837.995      143391.566
     1964103.832      143758.748
#Sta/Elev= 30
       0 2523.78      20 2516.23      40 2511.57      70 2496.73   119.9 2460.09
   129.9  2454.3   139.9 2452.33   199.8 2412.04   209.8 2404.12   219.8 2394.31
   229.8 2392.85   249.8 2374.75   259.8 2368.82   279.8  2360.8   309.8 2351.07
   339.7 2344.32   379.7 2331.71   389.7 2331.46   478.7 2341.97   557.5 2357.44
   616.6 2379.85   646.2 2389.57   675.8 2393.67   715.2 2404.13     725 2409.05
   744.7 2415.14   754.6  2417.5   764.4 2417.59   833.4 2439.91     863  2445.6
#Mann= 3 , 0 , 0
       0      .1       0   379.7    .045       0   389.7      .1       0
Bank Sta=379.7,389.7
XS Rating Curve= 0 ,0
Exp/Cntr=0.3,0.1

Type RM Length L Ch R = 1 ,2402.6  ,2391.4,2399.3,2388.5
XS GIS Cut Line= 3
     1963258.705      143547.459     1963679.106      143663.682
     1964048.242      143833.206
#Sta/Elev= 30
       0 2478.94     9.9 2470.59    79.3 2438.77    99.1 2426.52   138.8 2409.36
   178.4 2390.56   188.4  2384.6   257.7 2363.84   277.6 2355.54   327.1  2341.8
   356.9 2331.48   366.8 2330.53   430.2 2330.72   442.2  2330.6   465.9 2332.17
   495.6 2340.26   525.3 2351.45   535.2 2358.35   584.8 2376.97   604.6 2386.74
   614.5 2392.87   624.4 2402.14     664 2425.26   683.8 2436.04   703.7  2445.3
   713.6 2451.33   743.3 2460.85   792.8 2478.71   802.7 2480.96   842.4 2483.19
#Mann= 3 , 0 , 0
       0      .1       0   430.2    .045       0   442.2      .1       0
Bank Sta=430.2,442.2
XS Rating Curve= 0 ,0
Exp/Cntr=0.3,0.1

Chan Stop Cuts=-1
Use User Specified Reach Order=0
Composite Channel Slope=5